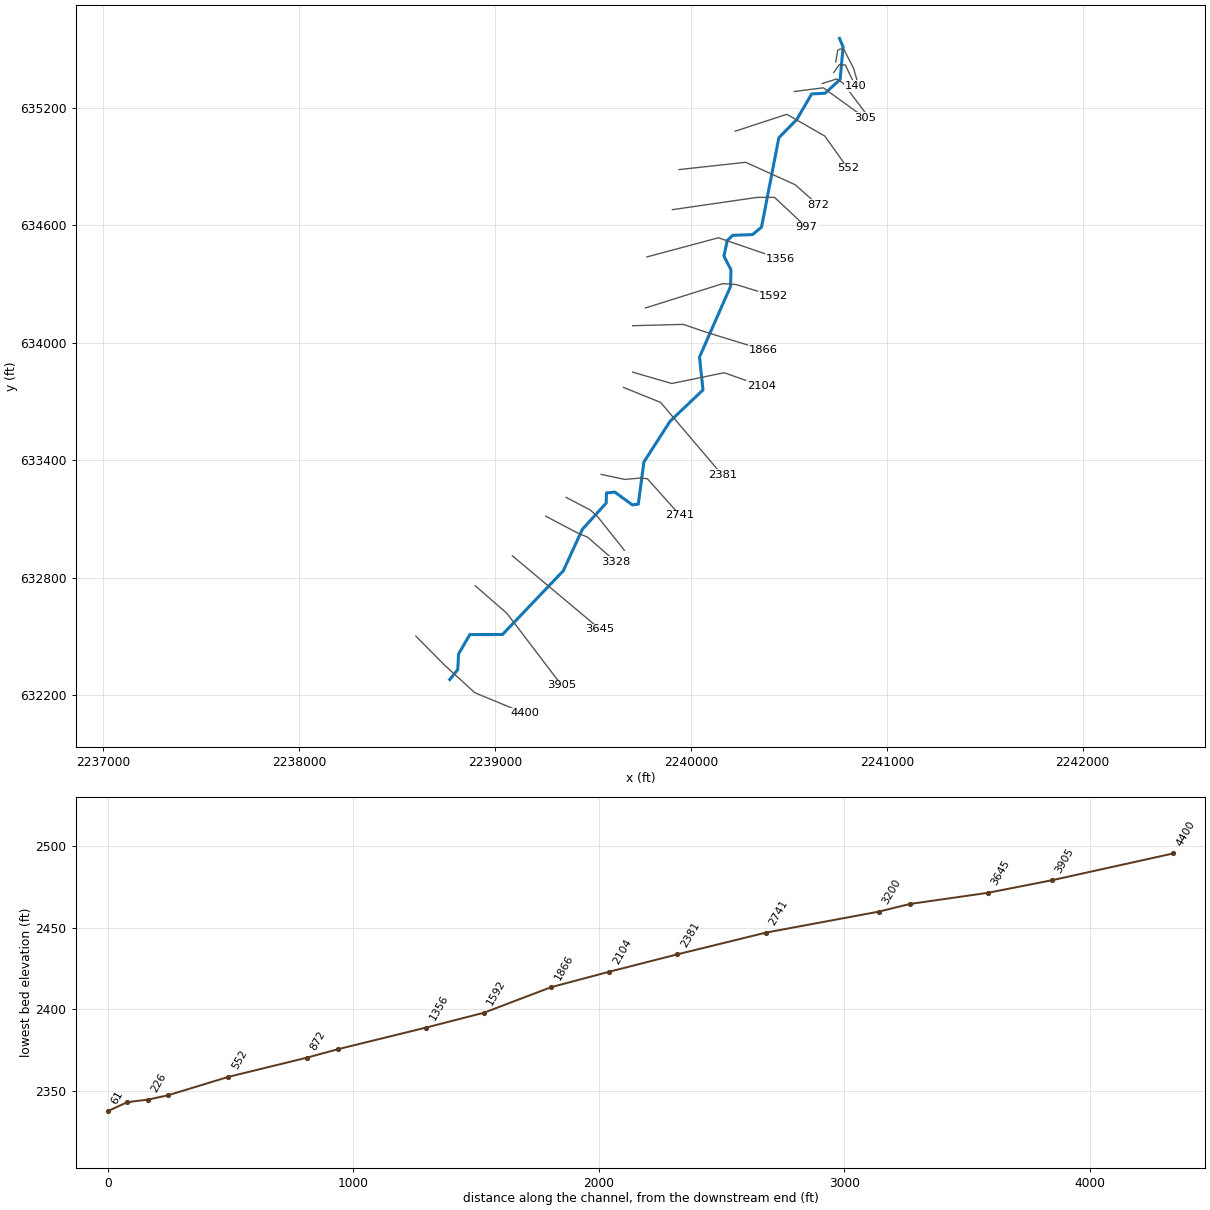
--- MTCHLCKFK.prj (project) ---

Proj Title=MTCHLCKFK
Current Plan=p01
Default Exp/Contr=0,0
English Units
Geom File=g01
Flow File=f01
Plan File=p01
BEGIN DESCRIPTION:
----------MODEL BY WSP USA 2022----------
AFH study
Randolph County, WV
HEC-RAS Version: RAS 6.2
Vertical Datum: NAVD88
Projection: NAD 1983 StatePlane West Virginia S FIPS 4702 (US Feet)
Terrain: 1-meter LIDAR (FEMA Region III 3DEP collected 2016-2018)
Land Use: 2019 NLCD
Hydrologic Method:
WV SIR2010-5033 regression equations
Additional Model Notes:
None
END DESCRIPTION:
DSS Export Rating Curves= 0
DSS Export Rating Curve Sorted= 0
DSS Export Volume Flow Curves= 0
DXF OffsetX= 0
DXF OffsetY= 0
DXF ScaleX= 0
DXF ScaleY= 0

--- MTCHLCKFK.p01 (plan) ---

Plan Title=Floodplain
Program Version=6.20
Short Identifier=Floodplain
Geom File=g01
Flow File=f01
Subcritical Flow
K Sum by GR= 0
Std Step Tol= 0.01
Critical Tol= 0.01
Num of Std Step Trials= 20
Max Error Tol= 0.3
Flow Tol Ratio= 0.001
Split Flow NTrial= 30
Split Flow Tol= 0.02
Split Flow Ratio= 0.02
Log Output Level= 0
Friction Slope Method= 1
Unsteady Friction Slope Method= 2
Unsteady Bridges Friction Slope Method= 1
Parabolic Critical Depth
Global Vel Dist= 0 , 0 , 0
Global Log Level= 0
CheckData=True
Encroach Param=-1 ,0,0, 0
Mapping Interval=1HOUR
Computation Time Step Use Courant=        0
Computation Time Step Use Time Series=    0
Computation Time Step Count To Double=0
Computation Time Step Max Doubling=0
Computation Time Step Max Halving=0
Computation Time Step Residence Courant=0
Run HTab= 0
Run UNet= 0
Run Sediment= 0
Run PostProcess= 0
Run WQNet= 0
Run RASMapper=-1
UNET Theta= 0
UNET Theta Warmup= 0
UNET ZTol= 0
UNET ZSATol= 0
UNET MxIter= 0
UNET Max Iter WO Improvement= 0
UNET MaxInSteps= 0
UNET DtIC= 0
UNET DtMin= 0
UNET MaxCRTS= 0
UNET WFStab= 0
UNET SFStab= 0
UNET WFX= 1
UNET SFX= 1
UNET Gravity=32.174
UNET 1D Methodology=Finite Difference
UNET DSS MLevel= 1
UNET Pardiso=0
UNET DZMax Abort= 0
UNET Use Existing IB Tables= 0
UNET Froude Reduction=False
UNET Froude Limit= 0
UNET Froude Power= 0
UNET D1 Cores= 0
UNET WindReference=Eulerian
UNET WindDragFormulation=Hsu (1988)
UNET D2 Coriolis=0
UNET D2 Cores= 0
UNET D2 Theta= 1
UNET D2 Theta Warmup= 1
UNET D2 Z Tol= 0.01
UNET D2 Volume Tol= 0.01
UNET D2 Max Iterations= 20
UNET D2 Equation= 0
UNET D2 RampUpFraction=0.1
UNET D2 TimeSlices= 1
UNET D2 Turbulence Formulation=Non-Conservative (original)
UNET D2 Eddy Viscosity=0.3
UNET D2 Transverse Eddy Viscosity=0.1
UNET D2 Smagorinsky Mixing=0
UNET D2 BCVolumeCheck=0
UNET D2 Cores=0
UNET D2 SolverType=PARDISO (Direct)
UNET D2 Minimum Iterations= 2147483647
UNET D2 Maximum Iterations= 2147483647
UNET D2 Restart Number= 10
UNET D2 Relaxation Coeff=1.3
UNET D2 SOR Precondition Iterations= 10
UNET D2 ILUT Maximum Fill= 8
UNET D2 ILUT Tolerance=1E-08
UNET D1D2 MaxIter= 0
UNET D1D2 ZTol=0.01
UNET D1D2 QTol=0.1
UNET D1D2 MinQTol=1
Write IC File= 0
Write IC File at Fixed DateTime=0
Write IC File at Sim End=0
Echo Input=False
Echo Parameters=False
Echo Output=False
Write Detailed= 0
HDF Write Warmup=0
HDF Write Time Slices=0
HDF Flush=0
HDF Compression= 1
HDF Chunk Size= 1
HDF Spatial Parts= 1
HDF Use Max Rows=0
HDF Fixed Rows= 1
Calibration Method= 0
Calibration Iterations= 20
Calibration Max Change=0.05
Calibration Tolerance=0.2
Calibration Maximum=1.5
Calibration Minimum=0.5
Calibration Optimization Method= 1
WQ AD Non Conservative
WQ ULTIMATE=-1
WQ Max Comp Step=1HOUR
WQ Output Interval=15MIN
WQ Output Selected Increments= 0
WQ Output face flow=0
WQ Output face velocity=0
WQ Output face area=0
WQ Output face dispersion=0
WQ Output cell volume=0
WQ Output cell surface area=0
WQ Output cell continuity=0
WQ Output cumulative cell continuity=0
WQ Output face conc=0
WQ Output face dconc_dx=0
WQ Output face courant=0
WQ Output face peclet=0
WQ Output face adv mass=0
WQ Output face disp mass=0
WQ Output cell mass=0
WQ Output cell source sink temp=0
WQ Output nsm pathways=0
WQ Output nsm derived pathways=0
WQ Create Restart=0
WQ Fixed Restart=0
WQ System Summary=0
WQ Write To DSS=0
Sorting and Armoring Iterations= 10
XS Update Threshold= 0.02
Bed Roughness Predictor= 0
Hydraulics Update Threshold= 0.02
Energy Slope Method= 1
Volume Change Method= 1
Sediment Retention Method= 0
Sediment TS Multiplier= 1
Warm Up Method= 0
XS Weighting Method= 0
Number of US Weighted Cross Sections= 1
Number of DS Weighted Cross Sections= 1
Upstream XS Weight=0
Main XS Weight=1
Downstream XS Weight=0
Number of DS XS's Weighted with US Boundary= 1
Upstream Boundary Weight= 1
Weight of XSs Associated with US Boundary= 0
Number of US XS's Weighted with DS Boundary= 1
Downstream Boundary Weight= 0.5
Weight of XSs Associated with DS Boundary= 0.5
Percentile Method= 0
Sediment Output Level= 3
Mass or Volume Output= 0
Output Increment Type= 1
Profile and TS Output Increment= 1
Transport Output Increment 1
XS Output Flag= 0
XS Output Increment= 10
Read HDF5 Sediment Hotstart= 0
Sediment Hotstart Type= 0
Write Gradation File= 0
Read Gradation Hotstart= 0
Write HDF5 File= 1
Write Binary Output= 1
Write DSS Sediment File= 0
DSS Sediment Output Type= 1
SV Curve= 0
Specific Gage Flag= 0
Subcell Erosion Methods= 0
Subcell Deposition Methods= 0
Advection Scheme= 1
Matrix Solver= 0
Implicit Weighting Factor= 1
Maximum Outer Loop Convergence Iterations= 5
Convergence Maximum Absolute= 0.001
Convergence RMSE= 0.0001
Grain Fractions Max Abs Error= 0.001
Max Subgrid Regions= 1
Max Subgrid Length Scale= 3.402823E+38
Initial Layer Thickness= 3.402823E+38
Min Layer Thickness= 3.402823E+38
Max Layer Thickness= 3.402823E+38
Number of Layers= 5

--- MTCHLCKFK.f01 (steady flow) ---

Flow Title=Flow
Program Version=6.20
Number of Profiles= 1
Profile Names=P100yr
River Rch & RM=MTCHLCKFK,Main,4400
     385
River Rch & RM=MTCHLCKFK,Main,1866
     430
Boundary for River Rch & Prof#=MTCHLCKFK,Main            , 1
Up Type= 0
Dn Type= 3
Dn Slope=0.03951
DSS Import GetInterval= 0
DSS Import GetPeak= 0
DSS Import FillOption= 0

--- MTCHLCKFK.g01 (geometry) ---

Geom Title=Geometry
Program Version=6.20

River Reach=MTCHLCKFK       ,Main
Reach XY= 30
2238768.81710801632281.4678946732238809.68235943632331.857324257
2238813.87635152632411.5431741772238871.19424354632510.800987184
2239038.25492887632511.4999858742239348.50900002632836.414000005
 2239445.9016214633048.4734227972239567.43100001      633182.206
2239568.96800001633233.989000008      2239611.23633238.447999999
2239701.58300005633172.5750000032239731.36200003633176.980000019
2239760.03199999633392.1710000192239893.71300001633600.070000008
     2240061.682633759.7929999982240043.88600001633927.761000022
2240202.39400004634288.2650000012240204.47699998634373.160999998
2240168.53900003634442.9520000222240185.74900003634523.067000017
2240213.33100003634549.2020000222240314.30900002      634552.816
2240360.60600004634590.956000015     2240448.748635047.119000003
2240540.41400003 635140.348000022240616.45600003635271.077000022
2240684.81300002635274.4109999982240761.76800001635344.515000016
2240776.87268759635510.6607987582240758.53167532 635554.70849964

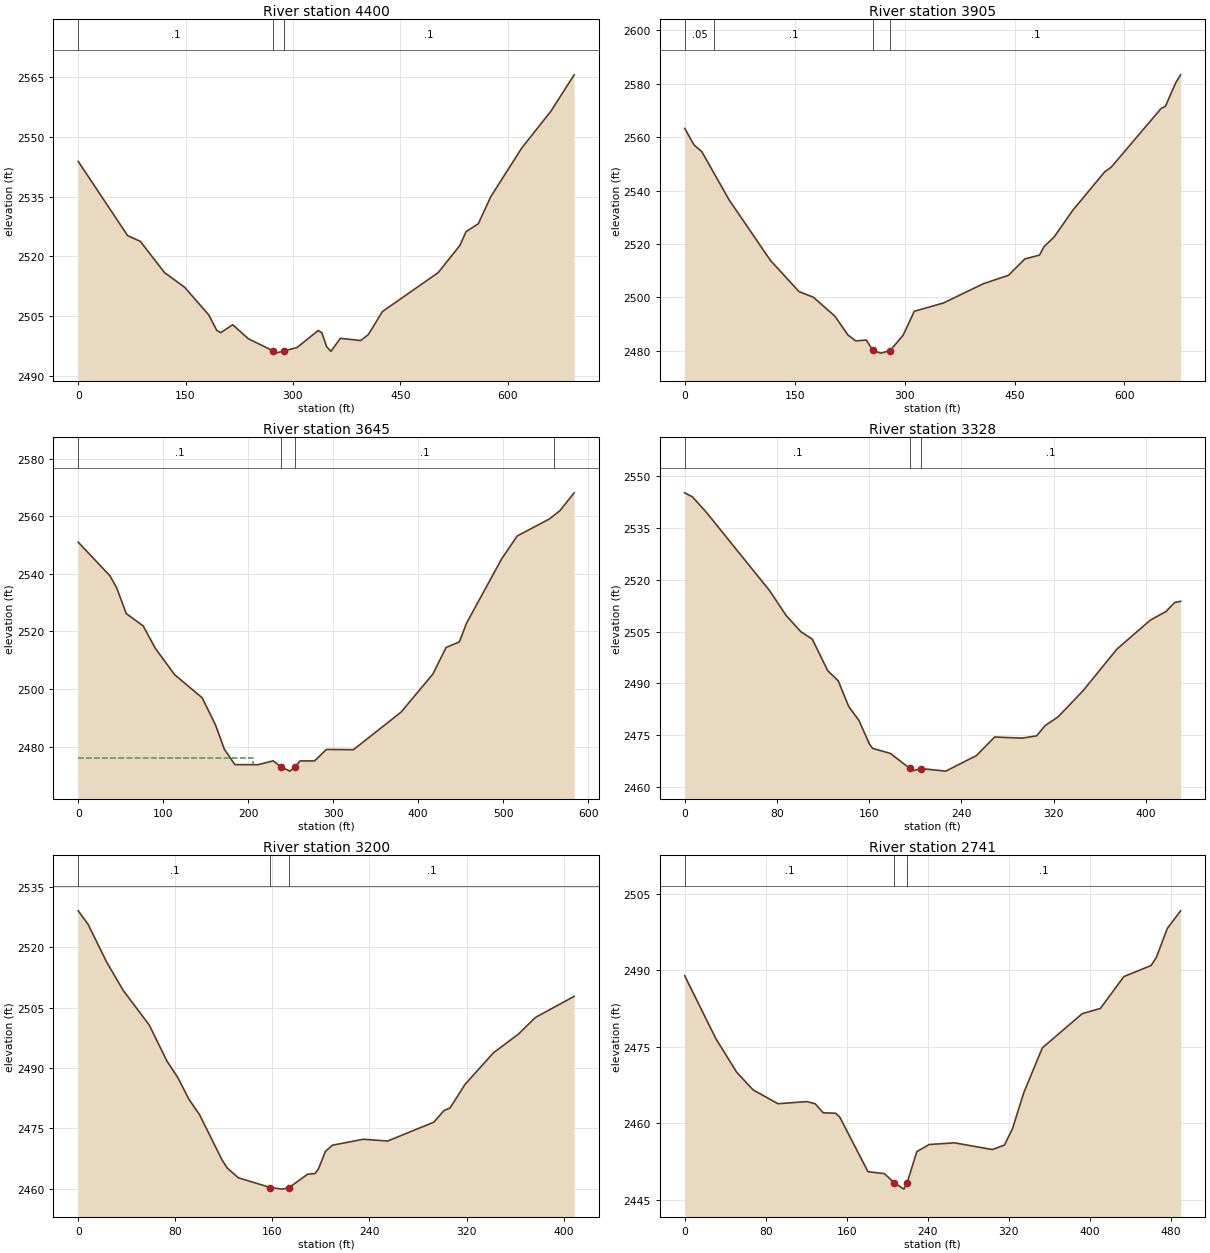
Type RM Length L Ch R = 1 ,4400    ,489.6,495.4,485.7
XS GIS Cut Line= 4
2238596.07900211632502.8694495762238743.94470412 632353.50601658
2238897.07155165632213.8871307862239151.82519821632108.669976272
#Sta/Elev= 30
       0 2543.84    69.1 2525.17    86.8 2523.73   120.6 2515.89   148.7 2512.19
   182.5 2505.22   193.7 2501.33   199.3 2500.78   215.9 2502.78   237.6 2499.27
  272.24  2496.2     276 2495.63   287.8 2496.21   305.6 2497.02   335.3 2501.32
   340.4 2500.79   347.2 2497.22   353.1 2496.09   366.3 2499.35   394.7  2498.8
   405.4 2500.29   425.1 2506.09     503 2515.87   533.3  2522.7   541.9 2526.15
   559.2 2528.19   576.4 2534.94   619.8 2547.21   660.3  2556.4     693  2565.6
#Mann= 3 ,-1,0
       0      .1       0  272.24    .045       0   287.8      .1       0
Bank Sta=272.24,287.8
XS Rating Curve= 0 ,0
Exp/Cntr=0.3,0.1

Type RM Length L Ch R = 1 ,3905    ,257.3,260.1,262.1
XS GIS Cut Line= 3
2238898.49935344632760.5452584672239060.60172972632619.387097023
 2239340.1327713632252.001090093
#Sta/Elev= 30
       0 2563.26    12.8 2557.08    23.4 2554.57    60.6 2536.53     117 2513.87
     156  2502.2   175.7 2500.06   204.9 2493.01   222.7 2485.98   233.3 2483.74
   247.9 2484.05   256.72480.144   267.6 2479.16   280.3 2480.09   298.1  2485.9
   313.3 2494.83     353 2497.92   407.5 2505.14   441.7 2508.28     464 2514.41
   484.1 2515.85   490.2 2518.98   504.2  2522.7   529.3 2532.56     573 2547.01
   581.6 2548.66   650.1 2570.76   655.8 2571.53   670.1 2580.45   676.6 2583.32
#Mann= 4 ,-1,0
       0     .05       0      40      .1       0   256.7    .045       0
   280.3      .1       0
Bank Sta=256.7,280.3
XS Rating Curve= 0 ,0
Exp/Cntr=0.3,0.1

Type RM Length L Ch R = 1 ,3645    ,314.5,316.8,318.6
BEGIN DESCRIPTION:
Structure XS 4
END DESCRIPTION:
XS GIS Cut Line= 2
2239088.33987116632913.1331519732239535.76274925632538.354578815
#Sta/Elev= 30
       0 2550.98    37.3 2539.34    45.3 2535.11    56.6 2526.17    76.5  2521.9
    90.7 2514.15   113.4 2504.99   145.9 2496.93   161.7 2487.42     172 2479.06
   184.4 2473.73   211.7 2473.71   229.4 2475.05   238.32473.014   249.1 2471.47
   255.3    2473   261.1 2475.01   278.1 2475.02     292    2479   323.9 2478.92
   379.9 2491.96   417.3 2505.17   432.9 2514.42   448.5 2516.35     457 2522.88
   498.3  2545.2   516.6 2553.15   554.3 2559.02   566.8 2561.93   583.6 2568.13
#Mann= 4 ,-1,0
       0      .1       0   238.3    .045       0   255.3      .1       0
     560     .08       0
#XS Ineff= 2 , 0
          205.14 2476.09
Permanent Ineff=
       F       F
Bank Sta=238.3,255.3
XS Rating Curve= 0 ,0
Exp/Cntr(USF)=0,0
Exp/Cntr=0.3,0.1

Type RM Length L Ch R = 1 ,3328    ,129.6,127.7,125.5
BEGIN DESCRIPTION:
Structure XS 3
END DESCRIPTION:
XS GIS Cut Line= 4
2239258.36669363633115.5308082352239426.82718515633026.771209961
2239472.50894228 633008.326794662239616.04103767632883.183466964
#Sta/Elev= 30
       0  2545.1     6.6 2543.98    17.9 2539.84    73.7 2516.81    87.9 2509.68
   100.8 2504.94   110.6 2502.83   124.1 2493.67   133.2 2490.75   142.3  2483.3
   151.2 2479.28   160.3 2472.44     163 2471.23   178.4 2469.77  195.38 2465.41
   198.8 2464.82   204.8  2465.4   226.4 2464.65     253 2469.14   268.8 2474.51
   292.7 2474.19   305.3 2474.86   312.5  2477.8   323.9 2480.35   345.4 2487.86
   374.9 2499.94   403.7 2508.27   417.4  2510.8     425 2513.42   430.1 2513.73
#Mann= 3 ,-1,0
       0      .1       0  195.38    .045       0   204.8      .1       0
Bank Sta=195.38,204.8
XS Rating Curve= 0 ,0
Exp/Cntr(USF)=0,0
Exp/Cntr=0.3,0.1

Type RM Length L Ch R = 1 ,3200    ,456.6,458.7,462.9
BEGIN DESCRIPTION:
Structure XS 2
END DESCRIPTION:
XS GIS Cut Line= 4
2239363.32447599 633211.287370372239486.54437846633146.608835641
2239523.30708148 633113.502795912239660.11323877632941.083363815
#Sta/Elev= 30
       0 2529.07     8.1 2525.75    23.5 2516.32    37.1 2509.29    58.5 2500.72
    73.2 2491.71    82.3 2487.54    91.3 2482.22     100 2478.42   118.4 2467.25
   122.9 2465.14     132 2462.74   158.3 2460.32   168.3 2459.92  173.86 2460.32
     189 2463.62   195.2 2463.79     198 2464.95   203.7 2469.28   209.4 2470.83
     235 2472.32     255 2471.87     293 2476.55   301.4 2479.43   306.5 2480.11
   318.7 2485.92   342.2  2493.8   362.7 2498.42   376.7 2502.56   408.7 2507.82
#Mann= 3 ,-1,0
       0      .1       0   158.3    .045       0  173.86      .1       0
Bank Sta=158.3,173.86
XS Rating Curve= 0 ,0
Exp/Cntr(USF)=0,0
Exp/Cntr=0.3,0.1

Type RM Length L Ch R = 1 ,2741    ,365.3,360.8,353.6
BEGIN DESCRIPTION:
Structure XS 1
END DESCRIPTION:
XS GIS Cut Line= 5
2239542.00302992633328.5618538262239663.32588138633302.907217658
2239738.20911109 633309.764230442239777.32997074633306.820452726
2239944.98647239 633119.35969832
#Sta/Elev= 30
       0 2488.93    30.8 2476.59    51.3 2470.03    67.6 2466.54    92.2 2463.83
   120.8 2464.25   128.9 2463.82   136.9 2462.05     149 2461.97     153 2461.29
   181.1  2450.5   197.2 2450.14     207 2448.35   216.5 2447.09  219.77 2448.35
   229.3 2454.44   241.6 2455.84   266.7 2456.16   303.9 2454.85   315.8 2455.72
   323.8 2458.92   335.1 2466.07   353.3 2474.78   392.7 2481.48   410.7 2482.52
   433.8 2488.75   460.7 2490.92     466 2492.54   476.7 2498.18   489.9 2501.64
#Mann= 3 ,-1,0
       0      .1       0     207    .045       0  219.77      .1       0
Bank Sta=207,219.77
XS Rating Curve= 0 ,0
Exp/Cntr(USF)=0,0
Exp/Cntr=0.3,0.1

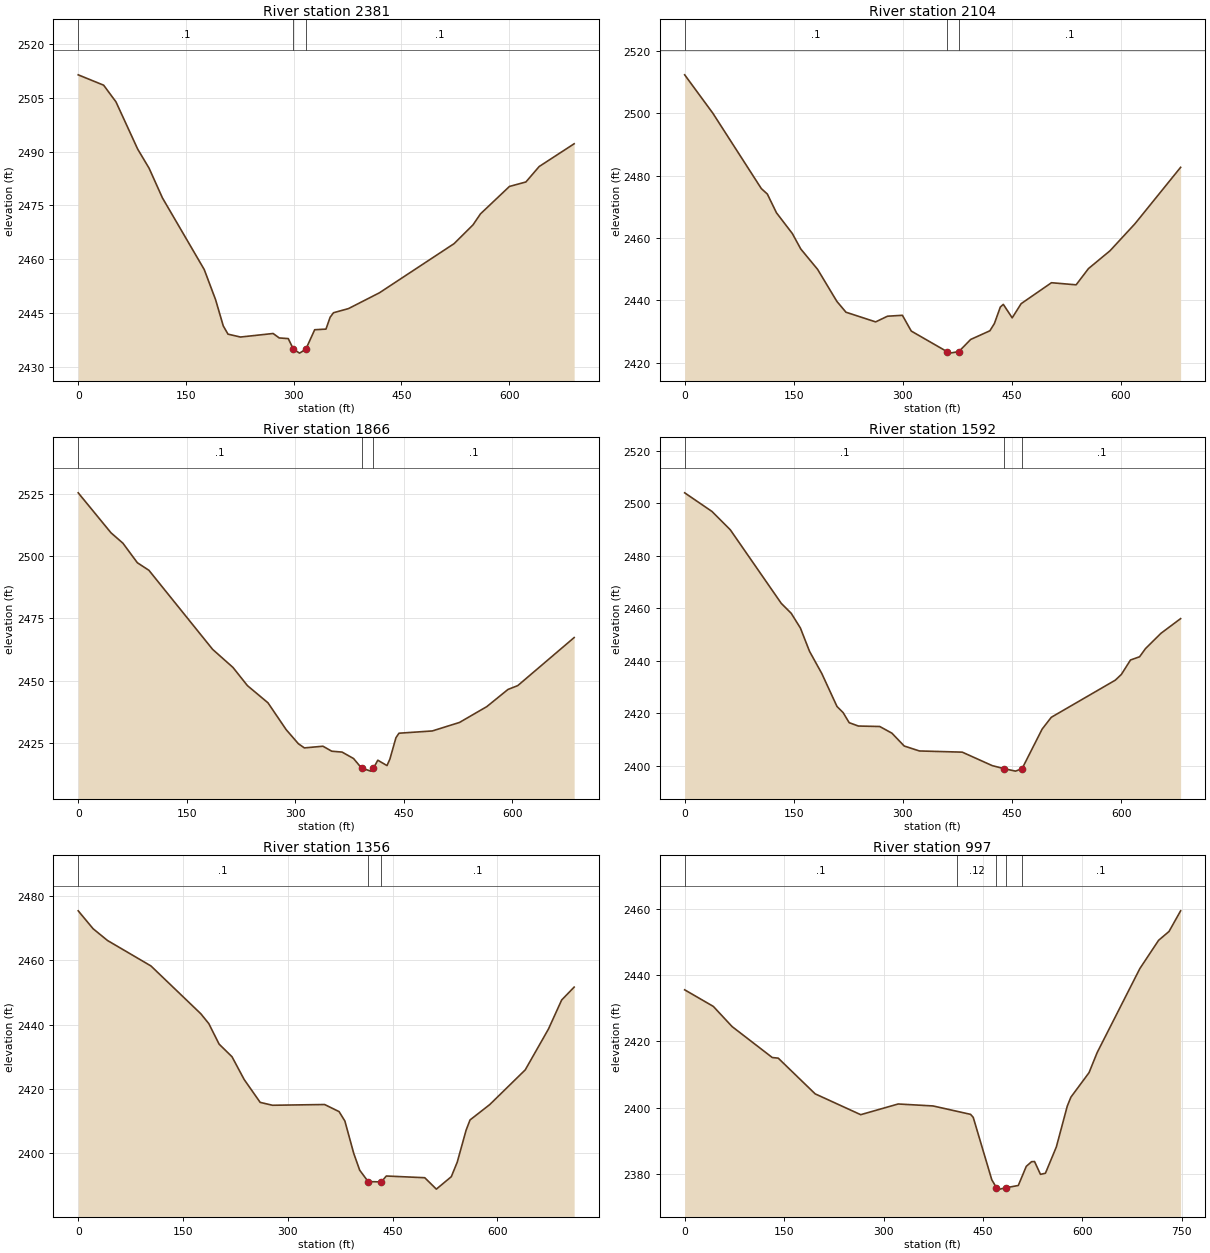
Type RM Length L Ch R = 1 ,2381    ,265.6,277,283.3
XS GIS Cut Line= 3
2239655.37630822633772.7973383192239845.12762066633696.183459075
2240159.67044393633325.759681042
#Sta/Elev= 30
       0 2511.41    35.4 2508.52    52.6 2503.86    82.8 2490.69    98.7 2485.35
   117.3 2477.06   175.5 2457.07   191.3 2448.66     202 2441.34   208.6 2439.04
     226 2438.24   271.4 2439.23   279.9 2437.99   292.5  2437.8   299.7 2434.84
   308.2 2433.75   316.92434.814   329.3 2440.28     345 2440.45   350.8 2443.76
   355.5 2445.02   376.4 2446.18   419.5 2450.59   523.4  2464.3   549.7 2469.53
   560.2 2472.62   600.5 2480.26   623.4 2481.51   641.9 2485.82   690.6 2492.17
#Mann= 3 ,-1,0
       0      .1       0   299.7    .045       0   316.9      .1       0
Bank Sta=299.7,316.9
XS Rating Curve= 0 ,0
Exp/Cntr=0.3,0.1

Type RM Length L Ch R = 1 ,2104    ,242.2,237.1,234.2
XS GIS Cut Line= 4
2239702.96517409633850.5534238562239902.07660988633792.603080606
2240169.53973257633847.5816113822240359.73573093633780.715830708
#Sta/Elev= 30
       0 2512.29    38.8 2499.97   105.4 2475.84   113.7 2474.08   126.2 2468.09
   148.1 2461.42   159.6  2456.5   182.8 2449.95   209.3 2439.69   221.8 2436.22
   262.6 2433.12   278.9 2434.94   299.4 2435.23   311.6 2430.18   360.6 2423.61
   364.7 2423.11   376.9 2423.59   393.3 2427.49   419.7 2430.27   425.9 2432.59
   434.1 2437.89   438.2 2438.73   450.4 2434.42   462.7 2438.96   504.4 2445.67
   538.3    2445   555.3  2450.2     585 2455.93   619.3 2464.59     682 2482.65
#Mann= 3 ,-1,0
       0      .1       0   360.6    .045       0   376.9      .1       0
Bank Sta=360.6,376.9
XS Rating Curve= 0 ,0
Exp/Cntr(USF)=0,0
Exp/Cntr=0.3,0.1

Type RM Length L Ch R = 1 ,1866    ,270.4,274.6,277.2
XS GIS Cut Line= 4
2239702.49010307634087.6379219182239961.41093145634094.432373885
2240077.85329101634054.4028583162240367.57129224633965.414482855
#Sta/Elev= 30
       0 2525.51    45.3 2509.44    61.8 2505.25    81.7 2497.41    97.7 2494.36
   185.7 2462.58   213.8 2455.32   233.8    2448   262.2 2441.09   287.3 2430.31
   304.2 2424.64   312.5 2422.97   338.1 2423.64   350.3 2421.64   364.6 2421.28
   380.4  2418.7   391.4 2414.88   404.2 2413.63  407.94 2414.82   413.9 2418.02
   426.6 2415.86   430.6 2418.45     439 2427.07   443.2 2428.87   489.2 2429.78
   526.8  2433.2   564.5 2439.56   593.8 2446.47   607.3 2448.01   685.2 2467.32
#Mann= 3 ,-1,0
       0      .1       0   391.4    .045       0  407.94      .1       0
Bank Sta=391.4,407.94
XS Rating Curve= 0 ,0
Exp/Cntr=0.3,0.1

Type RM Length L Ch R = 1 ,1592    ,236.1,235.6,232.6
XS GIS Cut Line= 4
2239768.41317038634178.3450421112240161.79695695634302.283367181
2240229.46621424 634298.217115122240422.02514907634238.689228363
#Sta/Elev= 30
       0 2504.06    37.5 2496.96    62.7 2489.97   132.8  2461.9   146.5  2458.1
   159.1 2452.49   171.7 2443.57   188.5 2435.15   209.4 2422.57   217.8 2420.24
   226.2 2416.38   238.8 2415.11   268.2 2414.93   284.9 2412.39   301.8 2407.49
   322.7  2405.6   381.6 2405.15   422.8 2400.01   439.62398.813   454.9 2397.91
   463.92398.875   491.4 2413.93     504 2418.44     592  2432.6   600.3 2434.78
   612.9  2440.3   625.4 2441.53   633.5 2444.64   654.7 2450.46   681.8 2456.08
#Mann= 3 ,-1,0
       0      .1       0   439.6    .045       0   463.9      .1       0
Bank Sta=439.6,463.9
XS Rating Curve= 0 ,0
Exp/Cntr=0.3,0.1

Type RM Length L Ch R = 1 ,1356    ,358,359.1,360.8
XS GIS Cut Line= 3
2239775.60166122634438.8618841362240140.72787286634536.640252071
2240454.35177784634428.668639068
#Sta/Elev= 30
       0  2475.4    21.3 2469.83      42 2466.16   104.1 2458.25   175.5 2443.37
   186.9 2440.31   201.6 2433.94   220.1    2430   237.5 2422.92   260.4 2415.81
     278 2414.91   352.6 2415.14   373.3 2412.94   381.6 2410.01   394.3 2399.93
   402.8 2394.72   414.9 2391.16   433.8 2391.07   440.9  2392.9   495.9 2392.37
   512.5 2388.82   533.9 2392.69   542.4 2397.21   555.1 2407.17   560.7 2410.34
   588.9 2415.12   639.7 2425.92     673 2438.65   691.8 2447.65   709.7 2451.67
#Mann= 3 ,-1,0
       0      .1       0   414.9    .045       0   433.8      .1       0
Bank Sta=414.9,433.8
XS Rating Curve= 0 ,0
Exp/Cntr(USF)=0,0
Exp/Cntr=0.3,0.1

Type RM Length L Ch R = 1 ,997     ,128.3,124.9,121.1
XS GIS Cut Line= 4
2239905.44686162634680.1021575022240338.94617089634742.830183026
2240426.94231307  634742.84968332240588.94659372634591.122074097
#Sta/Elev= 30
       0 2435.55    43.2 2430.56    71.5 2424.49   132.1 2415.17   141.1 2414.98
   196.8 2404.23   265.5 2397.96     322 2401.18   374.6 2400.59   431.2 2398.06
   435.2 2397.16   463.2 2378.37   470.3 2375.96   475.2 2375.55   484.9 2375.97
   503.2 2376.65   515.2  2382.4   523.2 2383.81   527.7 2383.86   536.6    2380
   544.1 2380.33   560.6 2388.27     577 2400.51   582.5 2403.23   609.9 2410.62
   622.1 2416.65   686.5 2441.94   714.8 2450.46   730.5 2453.11     748 2459.33
#Mann= 5 ,-1,0
       0      .1       0     410     .12       0   470.3    .045       0
   484.9     .12       0  508.01      .1       0
Bank Sta=470.3,484.9
XS Rating Curve= 0 ,0
Exp/Cntr(USF)=0,0
Exp/Cntr=0.3,0.1

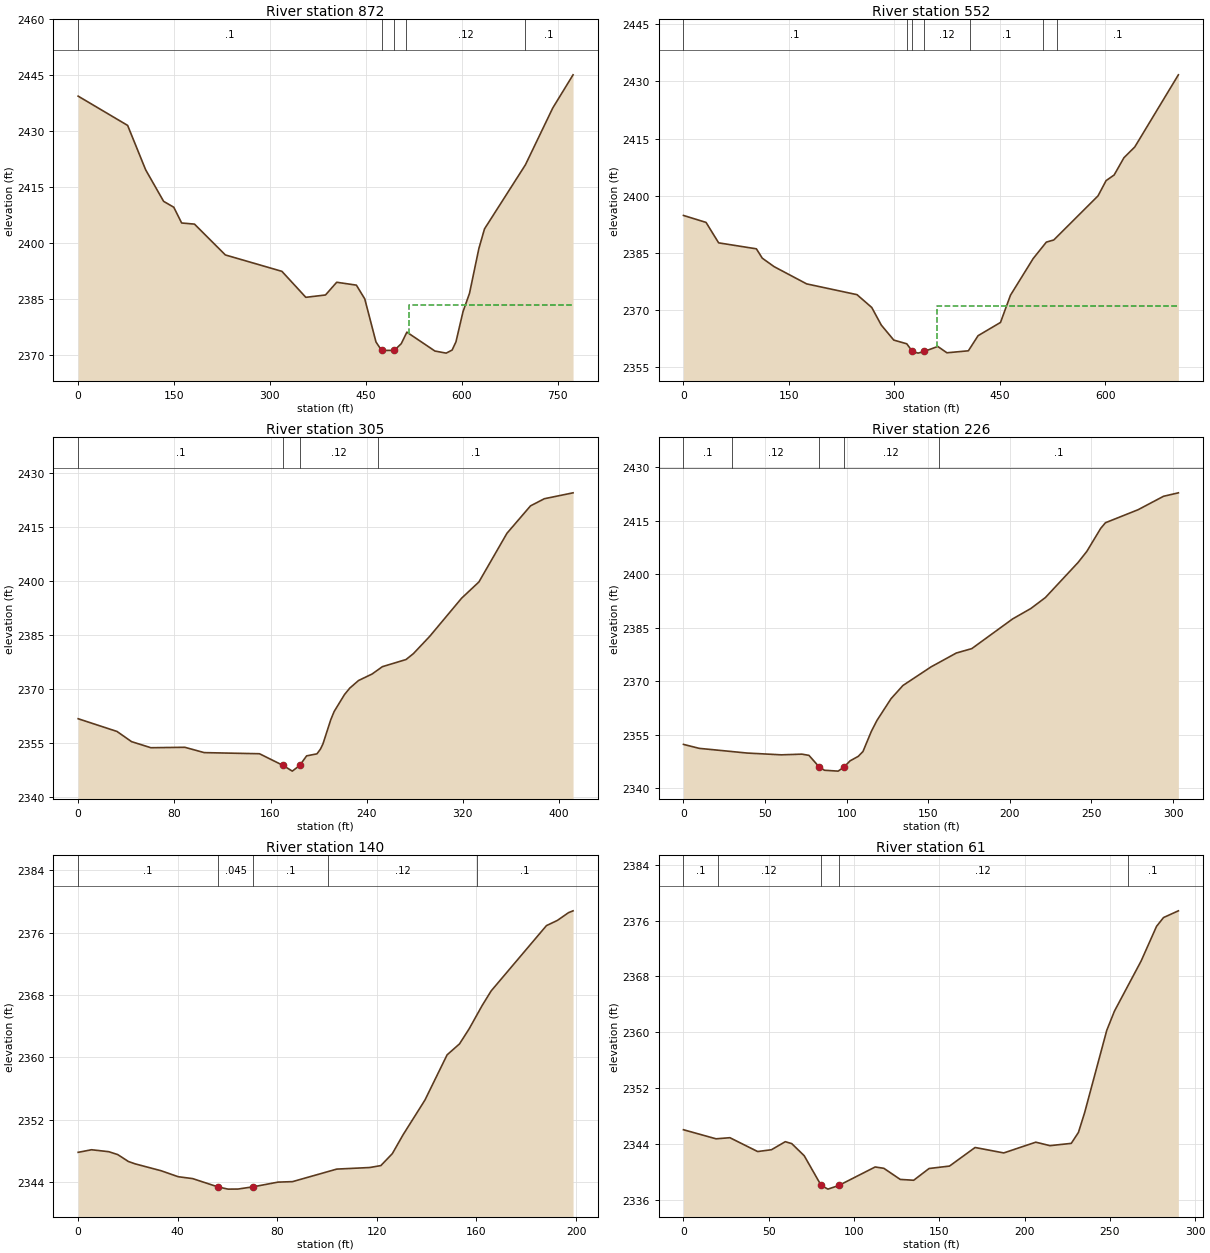
Type RM Length L Ch R = 1 ,872     ,320.3,320,318.9
XS GIS Cut Line= 4
2239939.22426581 634884.744164942240279.49679412 634921.89182087
2240532.10085445634807.4770406062240648.00154095 634704.94951024
#Sta/Elev= 30
       0 2439.35    77.4  2431.5   105.6 2419.59   133.7 2411.13   149.6 2409.55
   161.9 2405.32     182 2405.02   230.3 2396.75   318.8 2392.35   356.2 2385.38
     387 2386.01   404.5 2389.42   435.3 2388.65   448.4 2384.96     466 2373.38
   474.8 2371.13   494.5 2371.14   505.5 2372.94   514.3 2376.04   558.2 2370.97
   575.8 2370.41   585.1 2371.24   591.1 2373.44   602.1 2381.52   612.3 2386.46
   626.9 2398.44   635.7 2403.72   699.8 2420.94   742.5 2436.16   774.3 2445.07
#Mann= 5 ,-1,0
       0      .1       0   474.8    .045       0   494.5      .1       0
  512.29     .12       0   699.6      .1       0
#XS Ineff= 2 , 0
                          517.47         2383.42
Permanent Ineff=
       F       F
Bank Sta=474.8,494.5
XS Rating Curve= 0 ,0
Exp/Cntr(USF)=0,0
Exp/Cntr=0.3,0.1

Type RM Length L Ch R = 1 ,552     ,247.6,247.5,245.2
XS GIS Cut Line= 4
2240225.61826992635080.6590143172240489.72282966 635166.92341518
2240683.66329064635055.6233822172240801.04988338634890.687789889
#Sta/Elev= 30
       0  2394.8    32.1 2392.97      50  2387.6   103.7 2386.03   112.1 2383.57
   128.9 2381.35   175.2 2376.82   246.8 2373.99   267.8 2370.62   281.3 2366.01
   299.1 2362.06   317.6 2361.08   325.52359.103   333.7 2358.63   342.62359.085
   361.7 2360.38   374.7 2358.72   405.2 2359.24     419 2363.21   450.9 2366.69
   465.1 2373.85   497.4 2383.48   516.1 2387.79   526.7 2388.36   589.6 2399.94
   601.1 2403.95   612.5 2405.42   626.5 2409.97   641.9 2412.79   703.9 2431.74
#Mann= 7 ,-1,0
       0      .1       0  317.84     .12       0   325.5    .045       0
   342.6     .12       0  407.84      .1       0  511.44     .12       0
  531.44      .1       0
#XS Ineff= 2 , 0
                          361.01         2370.95
Permanent Ineff=
       F       F
Bank Sta=325.5,342.6
XS Rating Curve= 0 ,0
Exp/Cntr(USF)=0,0
Exp/Cntr=0.3,0.1

Type RM Length L Ch R = 1 ,305     ,77.9,78.7,78.9
XS GIS Cut Line= 3
2240528.16511123635283.262627334 2240675.9572711635302.237599924
2240888.69414143635148.326377135
#Sta/Elev= 30
       0 2361.82    32.3 2358.29    44.4 2355.46    60.5 2353.77    88.7 2353.89
   104.9 2352.41   150.8  2352.1   170.52348.839   178.1 2347.27   184.3 2348.86
     190 2351.51   198.6 2352.07   201.5 2353.38   203.6 2354.84   210.1 2361.56
   212.9 2363.83   221.5 2368.53   225.9 2370.33   233.2 2372.44   244.5 2374.25
     253 2376.28   272.7 2378.27   278.8  2379.9   292.4 2384.71   318.9  2395.3
   333.3 2399.81   356.6 2413.32   376.2 2420.94   387.7 2422.93   411.6 2424.57
#Mann= 4 ,-1,0
       0      .1       0   170.5    .045       0   184.3     .12       0
  249.01      .1       0
Bank Sta=170.5,184.3
XS Rating Curve= 0 ,0
Exp/Cntr(USF)=0,0
Exp/Cntr=0.3,0.1

Type RM Length L Ch R = 1 ,226     ,81.1,85.8,88.7
XS GIS Cut Line= 4
2240670.98185771635324.1169337922240743.76908848635347.269615055
2240777.26811722635325.3741633412240889.61285004635176.050329121
#Sta/Elev= 30
       0 2352.23     9.6 2351.12      39  2349.8      60  2349.3    72.6 2349.49
    76.9 2349.15    83.22345.887    86.4 2344.97    94.8 2344.73    98.4 2345.89
   102.1 2347.61   107.1 2348.87     110 2350.23   115.1 2355.85   118.6 2358.97
   127.2 2365.04   134.5 2368.75   151.7 2373.96   167.2 2377.85   176.7 2379.09
   201.7 2387.41   212.9 2390.34   221.8 2393.41   241.8 2403.23   247.2 2406.36
   255.7 2412.81   258.6 2414.39   278.6 2418.04   294.2 2421.81   303.3 2422.78
#Mann= 5 ,-1,0
       0      .1       0      30     .12       0    83.2    .045       0
    98.4     .12       0   156.4      .1       0
Bank Sta=83.2,98.4
XS Rating Curve= 0 ,0
Exp/Cntr(USF)=0,0
Exp/Cntr=0.3,0.1

Type RM Length L Ch R = 1 ,140     ,79.6,79.6,79.6
XS GIS Cut Line= 4
2240729.10332137635380.1656527462240757.50149847635420.734477168
2240788.26619032 635418.367962412240839.31529438635311.536724766
#Sta/Elev= 30
       0 2347.82     5.4 2348.15    12.3  2347.9    15.9 2347.53    20.2 2346.64
      23 2346.33    33.3 2345.46    40.2 2344.69      46 2344.45    56.1 2343.39
    60.2  2343.1    64.2 2343.11   70.35  2343.4    80.3    2344    86.1 2344.06
   103.9 2345.67   117.1 2345.87   121.6 2346.12   126.2 2347.65   130.5 2350.06
   139.3 2354.52   148.2 2360.32   153.2 2361.73   157.1 2363.68   162.2  2366.6
   165.9 2368.52   188.1 2376.89   192.5 2377.56     197 2378.56   198.8 2378.79
#Mann= 5 ,-1,0
       0      .1       0    56.1    .045       0   70.35      .1       0
  100.38     .12       0  160.38      .1       0
Bank Sta=56.1,70.35
XS Rating Curve= 0 ,0
Exp/Cntr(USF)=0,0
Exp/Cntr=0.3,0.1

Type RM Length L Ch R = 1 ,61      ,,,
XS GIS Cut Line= 6
2240739.09077093635434.350279314 2240749.5122553635493.931360819
2240762.28490477635500.3448145152240780.43657437635498.389455385
 2240830.0669382635402.9508111932240854.82997638635316.866983582
#Sta/Elev= 30
       0 2346.06    19.1 2344.76    27.2 2344.92    43.5 2342.94    51.6  2343.2
    59.7 2344.35    63.5 2344.07    70.8 2342.34    80.7  2338.1    84.7 2337.56
   91.04 2338.08   112.4 2340.73   117.5 2340.54   127.1 2338.95     135 2338.83
     144 2340.51     156 2340.86     171 2343.52   187.8 2342.74   206.6 2344.28
   214.9 2343.78   227.4 2344.11   231.6 2345.68   235.2 2348.48   248.2 2360.28
   252.7 2363.03   268.4 2370.23   277.4 2375.17   281.5 2376.43   290.2 2377.39
#Mann= 5 ,-1,0
       0      .1       0      20     .12       0    80.7    .045       0
   91.04     .12       0  260.61      .1       0
Bank Sta=80.7,91.04
XS Rating Curve= 0 ,0
Exp/Cntr(USF)=0,0
Exp/Cntr=0.3,0.1
LCMann Table=0

Chan Stop Cuts=-1
Use User Specified Reach Order=0
Composite Channel Slope=5